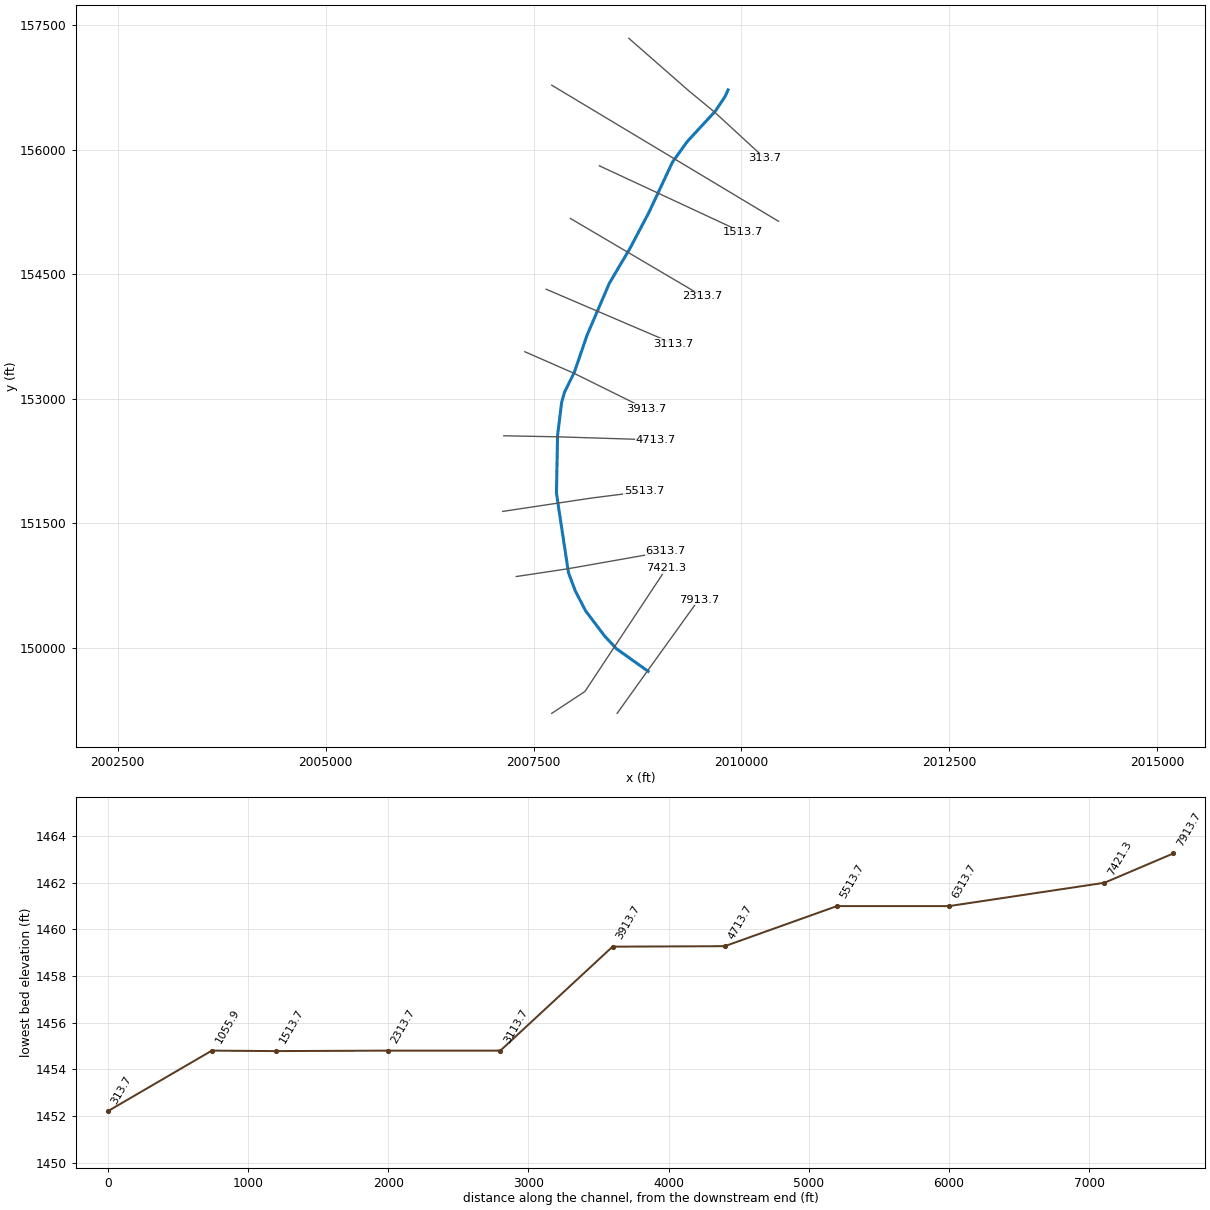
--- NwRvr.prj (project) ---

Proj Title=NwRvr
Current Plan=p01
Default Exp/Contr=0,0
English Units
Geom File=g01
Flow File=f01
Plan File=p01
BEGIN DESCRIPTION:
END DESCRIPTION:
DSS Export Rating Curves= 0
DSS Export Rating Curve Sorted= 0
DSS Export Volume Flow Curves= 0
DXF OffsetX= 0
DXF OffsetY= 0
DXF ScaleX= 0
DXF ScaleY= 0

--- NwRvr.p01 (plan) ---

Plan Title=Floodplain
Program Version=4.00
Geom File=g01
Flow File=f01
K Sum by GR=0
Std Step Tol=0.01
Critical Tol=0.01
Num of Std Step Trials=20
Max Error Tol=0.3
Flow Tol Ratio=0.001
Split Flow NTrial=30
Split Flow Tol=0.02
Split Flow Ratio=0.02
Log Output Level=0
Friction Slope Method=1
Unsteady Friction Slope Method=2
Unsteady Bridges Friction Slope Method=1
Global Log Level=0
CheckData=False
Run HTab=0
Run UNet=0
Run PostProcess=0
UNET Theta=0
UNET Theta Warmup=0
UNET ZTol=0
UNET ZSATol=0
UNET MxIter=0
UNET MaxInSteps=0
UNET DtIC=0
UNET DtMin=0
UNET MaxCRTS=0
UNET WFStab=0
UNET SFStab=0
UNET WFX=0
UNET SFX=0
UNET DSS MLevel=0
UNET DZMax Abort=0
UNET Convert EG Bridges=0
UNET Use Existing IB Tables=0
UNET Froude Limit=0
UNET Froude Power=0
Write IC File=0
Echo Input=False
Echo Output=False
Write Detailed=0

--- NwRvr.f01 (steady flow) ---

Flow Title=NFF Regression Equation
Program Version=4.10
Number of Profiles= 1
Profile Names=P100yr
River Rch & RM=NwRvr,Main            ,7913.7
  230000
River Rch & RM=NwRvr,Main            ,313.7
  230000
Boundary for River Rch & Prof#=NwRvr,Main            , 1
Up Type= 0
Dn Type= 3
Dn Slope=0.001167
DSS Import GetInterval= 0
DSS Import GetPeak= 0
DSS Import FillOption= 0

--- NwRvr.g01 (geometry) ---

Geom Title=USGS 3m DEM
Program Version=4.10

River Reach=NwRvr           ,Main
Reach XY= 22
     2008878.661      149718.717     2008515.876      149977.577
     2008497.964      149990.367     2008355.143      150143.673
     2008126.808      150446.438     2008001.267      150689.833
     2007919.833      150909.212     2007775.794      151863.751
     2007789.161      152561.469     2007838.473      152961.114
     2007874.302       153086.16      2007990.09      153319.738
     2008145.011      153771.681     2008411.965      154394.326
     2008657.378       154810.31     2008888.481      155248.898
     2009169.547      155851.448     2009344.398      156095.971
     2009359.704       156113.57     2009686.082      156467.686
     2009801.717      156641.699      2009838.86      156723.148

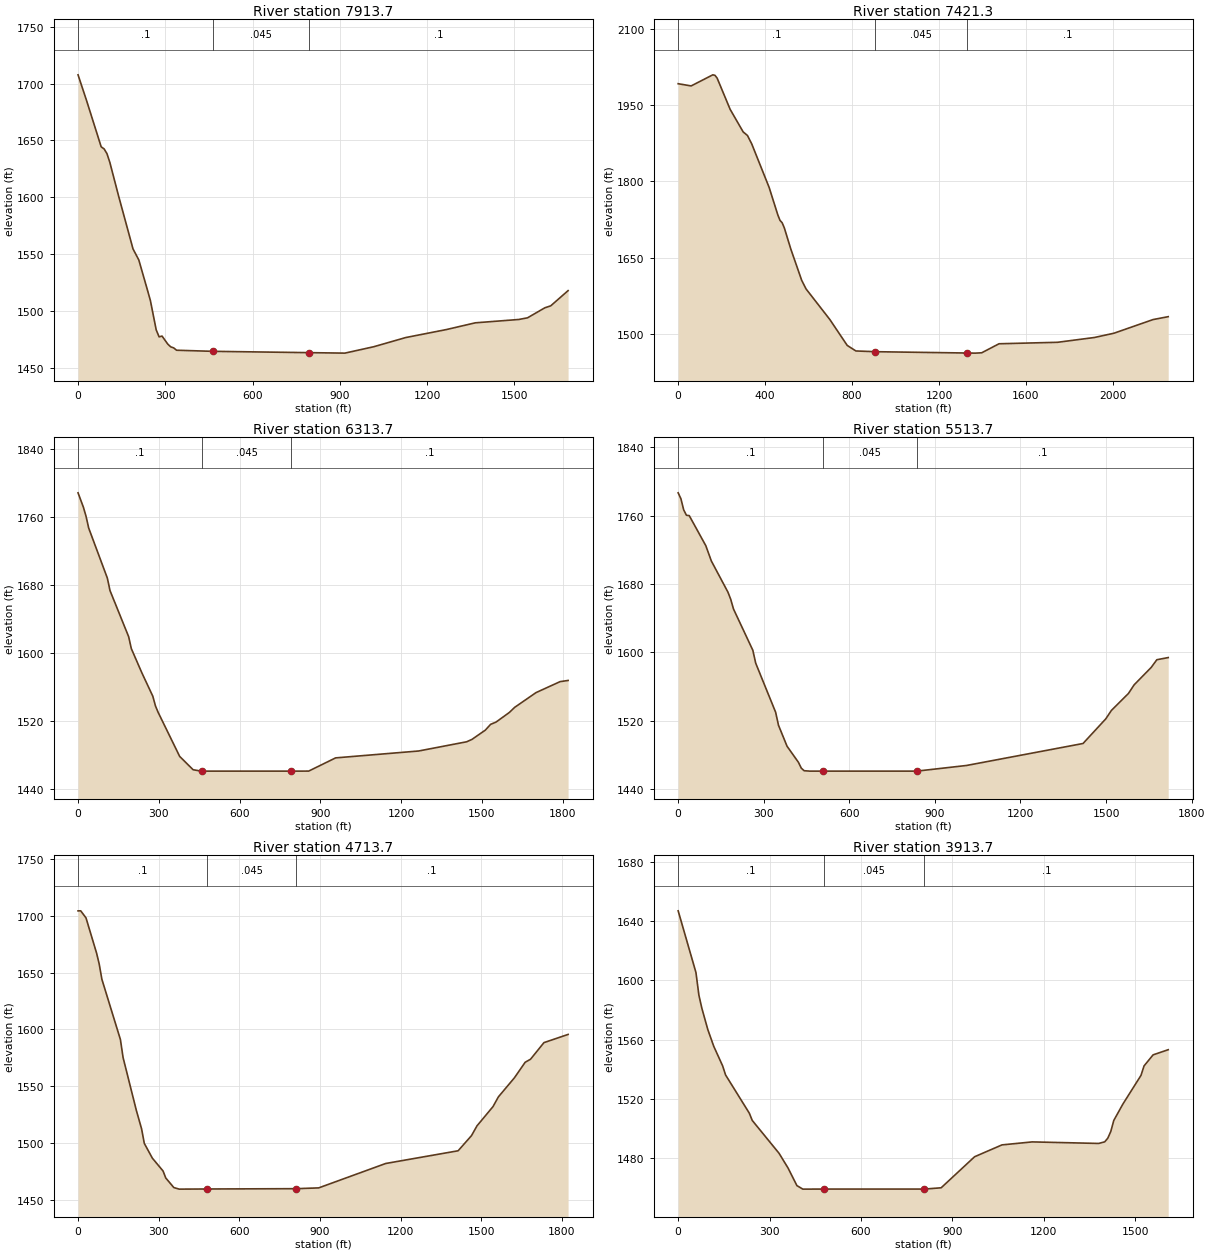
Type RM Length L Ch R = 1 ,7913.7  ,485.1,492.4,500.2
XS GIS Cut Line= 4
     2008505.531         149213.      2008632.67      149391.183
     2008870.521      149724.526     2009486.723      150582.971
#Sta/Elev= 30
       0 1707.62    29.8 1684.65    79.6  1644.4    89.6  1642.6    99.5  1638.4
   109.4 1630.68   139.3 1601.37     189 1554.78   208.9 1545.12   238.9 1518.46
   248.9  1509.3   268.8 1483.64   278.8 1477.54   288.8 1478.22   308.8 1471.12
   318.8 1468.76   328.8 1467.87   338.8  1465.8   463.4 1464.84   793.4 1463.68
   917.5 1463.26  1017.2  1468.9  1126.8 1476.94  1266.4 1483.94  1366.1 1489.87
  1515.6 1492.81  1545.5 1494.25  1605.4 1503.09  1625.3 1504.76  1685.1 1518.14
#Mann= 3 , 0 , 0
       0      .1       0   463.4    .045       0   793.4      .1       0
Bank Sta=463.4,793.4
XS Rating Curve= 0 ,0
Exp/Cntr=0.3,0.1

Type RM Length L Ch R = 1 ,7421.3  ,1259.5,1107.6,960.2
XS GIS Cut Line= 3
     2007719.317      149212.314     2008118.343      149476.285
     2009096.469      150958.821
#Sta/Elev= 30
       0 1991.75    59.8 1987.42   159.5 2009.23   169.4 2008.21   179.4 2002.69
   239.2 1941.34     299 1897.02     319 1889.89   338.9 1873.05   418.6 1787.76
   458.5 1733.79   468.5 1723.01   478.4 1718.38   488.4 1708.31   518.4 1666.53
   568.2 1605.28   588.2 1588.35     698 1528.01   777.8 1477.17   817.7 1466.25
   907.5 1464.81  1326.6 1462.22  1366.5    1462  1396.4 1462.64  1476.3 1480.41
  1745.7  1483.3  1915.3 1492.75  2005.1 1501.16  2184.7 1527.96  2254.6 1533.69
#Mann= 3 , 0 , 0
       0      .1       0   907.5    .045       0  1326.6      .1       0
Bank Sta=907.5,1326.6
XS Rating Curve= 0 ,0
Exp/Cntr=0.3,0.1

Type RM Length L Ch R = 1 ,6313.7  ,800,800,795.5
XS GIS Cut Line= 5
     2007292.797      150860.822     2007508.124      150893.315
     2007913.013      150954.412     2008316.425      151025.664
     2009088.284      151162.427
#Sta/Elev= 30
       0 1788.09    19.8 1771.28    29.7 1760.53    39.6 1746.67   108.9 1687.86
   118.8 1673.19   188.1 1618.95     198 1604.96   237.7 1576.13   277.7 1549.12
   287.7  1537.6   297.7 1530.01   377.6  1478.3   427.5 1462.63   457.5    1461
   462.2    1461   792.2    1461     857 1461.04     957 1476.56  1265.1 1484.64
  1443.7 1495.47  1463.6 1498.28  1513.2 1509.18    1533    1516  1552.9 1518.61
  1602.5 1529.94  1622.3 1535.95  1701.7  1553.3    1791 1566.17  1820.8 1567.56
#Mann= 3 , 0 , 0
       0      .1       0   462.2    .045       0   792.2      .1       0
Bank Sta=462.2,792.2
XS Rating Curve= 0 ,0
Exp/Cntr=0.3,0.1

Type RM Length L Ch R = 1 ,5513.7  ,830.5,800,767.3
XS GIS Cut Line= 5
     2007129.852      151645.291     2007388.728      151684.355
     2007793.644      151745.457      2008198.56      151806.558
     2008830.452      151886.813
#Sta/Elev= 30
       0 1786.87     9.7 1779.92    19.4 1766.91    29.1 1760.55    38.8 1760.22
      97 1724.91   116.4 1707.01   174.5 1670.58   184.2 1662.24   193.9  1650.9
   261.8 1602.48   271.8 1587.42   341.7 1529.93   351.7 1514.72   381.7 1490.14
   421.6 1471.34   431.6  1464.5   441.6 1461.48   461.6    1461   506.3    1461
   836.3    1461  1010.9 1467.62  1419.2 1493.36  1498.8 1522.15  1518.7  1532.1
  1578.4 1551.93  1598.3 1562.02  1658.1 1582.39    1678 1591.45  1717.8 1593.96
#Mann= 3 , 0 , 0
       0      .1       0   506.3    .045       0   836.3      .1       0
Bank Sta=506.3,836.3
XS Rating Curve= 0 ,0
Exp/Cntr=0.3,0.1

Type RM Length L Ch R = 1 ,4713.7  ,871.2,800,722.7
XS GIS Cut Line= 4
     2007142.942      152556.367     2007379.423      152551.836
     2007788.827      152543.993     2008965.507      152506.838
#Sta/Elev= 30
       0 1704.28     9.9 1704.32    29.6 1698.11      69 1667.08    78.8  1657.4
    88.7 1644.08   157.7 1590.96   167.5 1575.21   216.8 1528.73   236.5  1512.3
   246.5 1499.58   276.5 1486.56   316.4 1475.21   326.4  1469.1   356.4 1460.65
   376.4 1459.28     481  1459.4     811 1459.67   895.4 1460.37  1144.8 1481.86
  1414.2 1493.05  1464.1 1506.45  1484.1 1514.92  1543.9 1531.94  1563.9 1540.48
  1623.7 1557.34  1663.6 1570.98  1683.6 1573.67  1733.5 1588.28  1823.3 1595.49
#Mann= 3 , 0 , 0
       0      .1       0     481    .045       0     811      .1       0
Bank Sta=481,811
XS Rating Curve= 0 ,0
Exp/Cntr=0.3,0.1

Type RM Length L Ch R = 1 ,3913.7  ,798.4,800,810
XS GIS Cut Line= 5
      2007395.97      153568.759     2007609.815      153474.834
     2007985.233      153309.941     2008352.044      153128.108
     2008849.822      152881.353
#Sta/Elev= 30
       0  1646.9    58.4 1605.31    68.1 1589.98    77.8 1581.19    97.3 1566.87
   116.8 1555.58     146 1542.36   155.7 1536.22   233.6 1510.46   243.3 1505.55
   331.2 1483.42   360.5 1473.57   389.8 1461.63   409.3 1459.26   478.6  1459.3
   808.6  1459.3   863.3 1460.16   973.1  1481.1  1062.9 1489.08  1162.1  1491.1
  1380.4 1490.06  1400.2 1491.15  1410.2 1493.59  1420.1 1498.14    1430 1505.59
  1459.8  1516.6  1519.3 1535.97  1529.2  1542.3    1559 1549.79  1608.6 1553.26
#Mann= 3 , 0 , 0
       0      .1       0   478.6    .045       0   808.6      .1       0
Bank Sta=478.6,808.6
XS Rating Curve= 0 ,0
Exp/Cntr=0.3,0.1

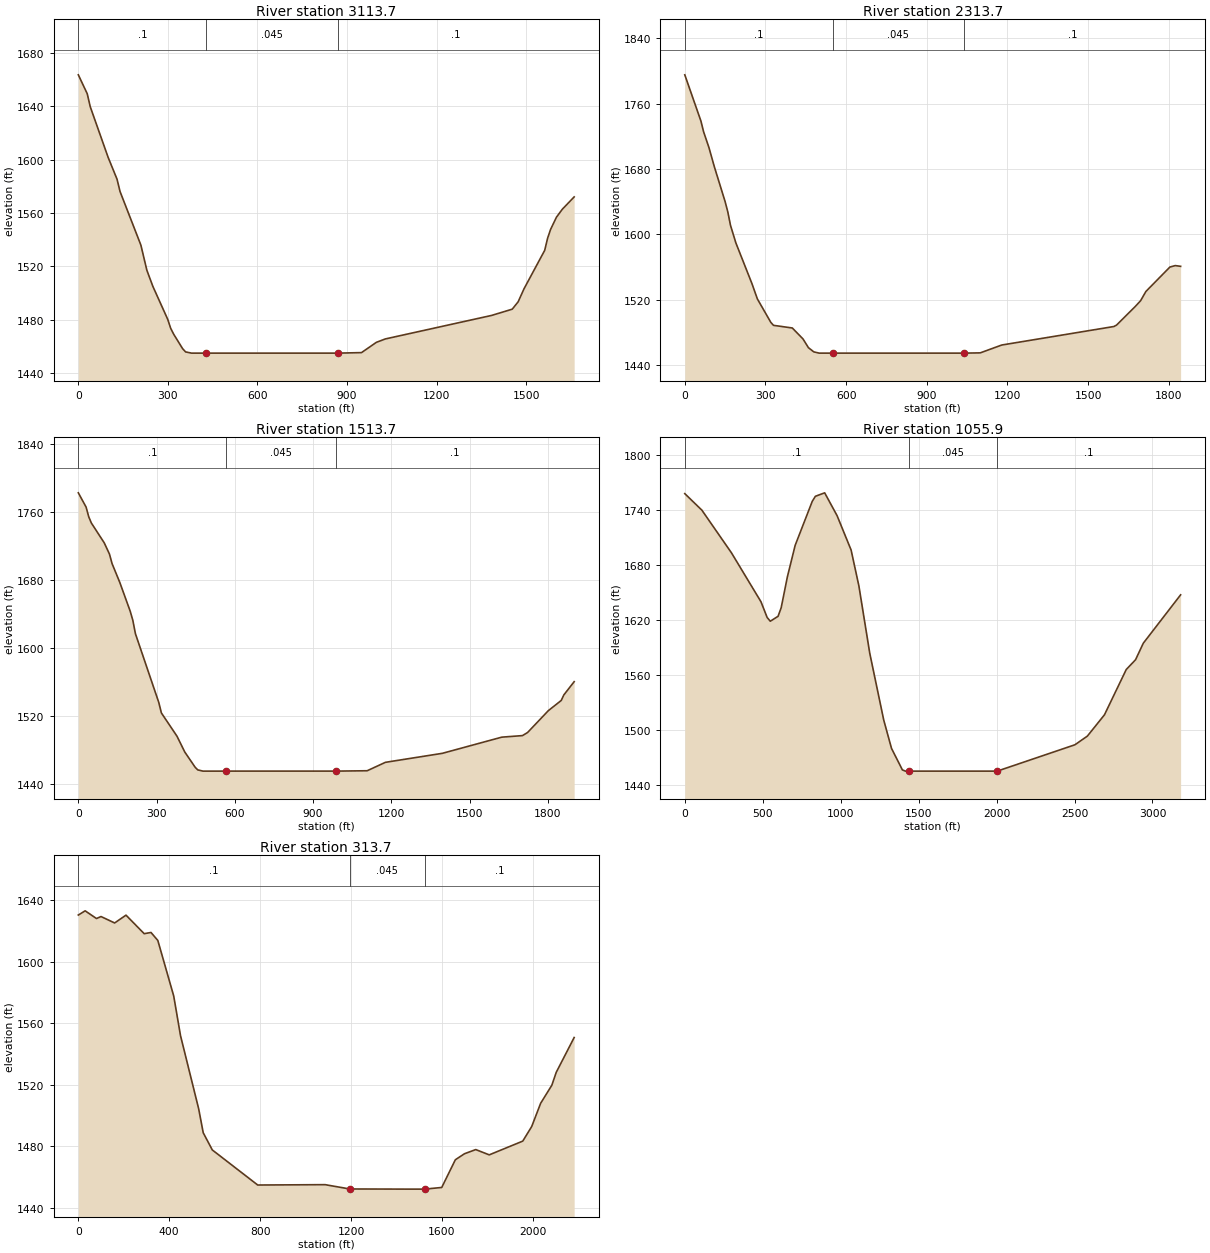
Type RM Length L Ch R = 1 ,3113.7  ,823.1,800,776.9
XS GIS Cut Line= 5
     2007652.828      154321.413     2007891.315      154219.164
     2008267.682      154057.799     2008644.048      153896.435
      2009179.52      153666.855
#Sta/Elev= 30
       0 1663.61    29.9 1649.38    39.9 1639.69    99.8 1601.72   129.7 1585.28
   139.7 1576.09   209.6 1535.82   229.5 1517.08   249.5 1504.99   299.4  1480.2
   309.4 1473.42   319.4 1469.02   349.4 1458.13   359.4 1455.72   379.3  1454.8
   429.3  1454.8   868.7  1454.8   948.6 1455.18   998.6 1462.91  1028.5 1465.44
  1384.6 1483.09  1453.7 1487.78  1473.5 1493.32  1493.2 1503.11  1562.4 1531.92
  1572.2 1541.06  1582.1 1547.61  1601.8 1556.79  1621.6  1562.8  1661.1 1572.02
#Mann= 3 , 0 , 0
       0      .1       0   429.3    .045       0   868.7      .1       0
Bank Sta=429.3,868.7
XS Rating Curve= 0 ,0
Exp/Cntr=0.3,0.1

Type RM Length L Ch R = 1 ,2313.7  ,782.6,800,817.4
XS GIS Cut Line= 5
     2007943.861      155174.208     2008279.716      154976.068
     2008632.412      154767.992     2008985.109      154559.916
     2009532.466      154236.999
#Sta/Elev= 30
       0 1795.37      60 1738.82      70 1725.62      90 1706.18     110  1682.8
     150 1640.21     160 1627.63     170  1611.2     190 1589.67     250 1539.72
     270 1521.14     320 1492.47     330  1488.8   399.9 1485.57   439.9 1472.09
   459.9 1461.48   479.8 1456.35   499.8  1454.8   549.8  1454.8  1039.2  1454.8
  1099.1 1455.12    1179 1464.71  1596.2 1487.37  1606.1 1489.09  1675.6 1511.83
  1695.5  1518.9  1715.4 1530.28  1804.7 1560.17  1824.6 1561.92  1844.5 1561.02
#Mann= 3 , 0 , 0
       0      .1       0   549.8    .045       0  1039.2      .1       0
Bank Sta=549.8,1039.2
XS Rating Curve= 0 ,0
Exp/Cntr=0.3,0.1

Type RM Length L Ch R = 1 ,1513.7  ,476.8,457.9,438.9
XS GIS Cut Line= 5
     2008291.602      155808.826     2008625.216      155653.208
     2008996.327      155480.099     2009367.438       155306.99
     2010014.045      155005.372
#Sta/Elev= 30
       0 1782.27    29.8 1765.46    39.8 1754.18    49.8 1746.83    99.5 1723.32
   119.4 1710.13   129.3 1699.02   159.2 1676.65     199 1642.81   208.9 1632.28
   218.9 1616.46   308.4 1535.58   318.4 1523.24   378.1 1495.93   408.1 1477.25
     448 1459.25     458  1456.2     478 1454.78   567.9  1454.8   987.4  1454.8
  1107.2 1455.22  1177.1 1465.13  1395.2 1475.72  1623.2 1494.76  1702.4 1496.58
  1722.2 1500.25  1801.5  1525.9  1851.1 1537.96    1861 1544.43  1900.6 1560.04
#Mann= 3 , 0 , 0
       0      .1       0   567.9    .045       0   987.4      .1       0
Bank Sta=567.9,987.4
XS Rating Curve= 0 ,0
Exp/Cntr=0.3,0.1

Type RM Length L Ch R = 1 ,1055.9  ,769.2,742.1,705.5
XS GIS Cut Line= 2
     2007719.317      156779.488     2010444.973      155140.412
#Sta/Elev= 30
       0 1758.05   109.7 1739.96   299.1 1693.43   488.6 1639.92   528.4 1622.66
   548.4 1618.63   598.2 1623.99   618.2 1633.33     658 1667.11   707.9 1701.52
   817.6 1749.62   837.5 1755.13   897.3 1758.94   977.1  1733.9  1066.8 1696.44
  1116.7 1657.24  1186.5  1583.6  1276.2 1510.55    1326 1479.66  1395.8 1456.14
  1415.8  1454.8  1435.7  1454.8    2004  1454.8  2502.6 1483.61  2582.3 1493.06
    2692 1516.36  2831.6 1565.82  2891.4 1576.54  2941.2 1594.62  3180.5 1647.47
#Mann= 3 , 0 , 0
       0      .1       0  1435.7    .045       0    2004      .1       0
Bank Sta=1435.7,2004
XS Rating Curve= 0 ,0
Exp/Cntr=0.3,0.1

Type RM Length L Ch R = 1 ,313.7   ,266.1,313.7,370.9
XS GIS Cut Line= 5
     2008646.286      157344.264     2009359.777      156718.063
      2009675.73      156456.455     2009976.752      156179.012
     2010280.457      155899.097
#Sta/Elev= 30
       0 1630.43      30 1633.17    79.9 1628.16    99.9 1629.45   159.9 1625.28
   209.8 1630.36   289.8 1618.31   319.8 1619.09   349.8 1613.91   419.7 1577.84
   449.7 1551.99   529.6 1504.42   549.6 1488.85   589.6 1477.67   789.4 1454.87
    1086  1455.1  1194.5  1452.3  1459.4  1452.2  1524.5 1452.21  1599.2 1453.28
  1659.1  1471.3    1699 1475.19  1748.9 1477.92  1808.2 1474.48  1955.7 1483.42
  1995.1 1492.91  2034.4    1508  2083.6 1519.75  2103.2 1528.19  2181.9 1550.78
#Mann= 3 , 0 , 0
       0      .1       0  1194.5    .045       0  1524.5      .1       0
Bank Sta=1194.5,1524.5
XS Rating Curve= 0 ,0
Exp/Cntr=0.3,0.1

Chan Stop Cuts=-1
Use User Specified Reach Order=0
Composite Channel Slope=5